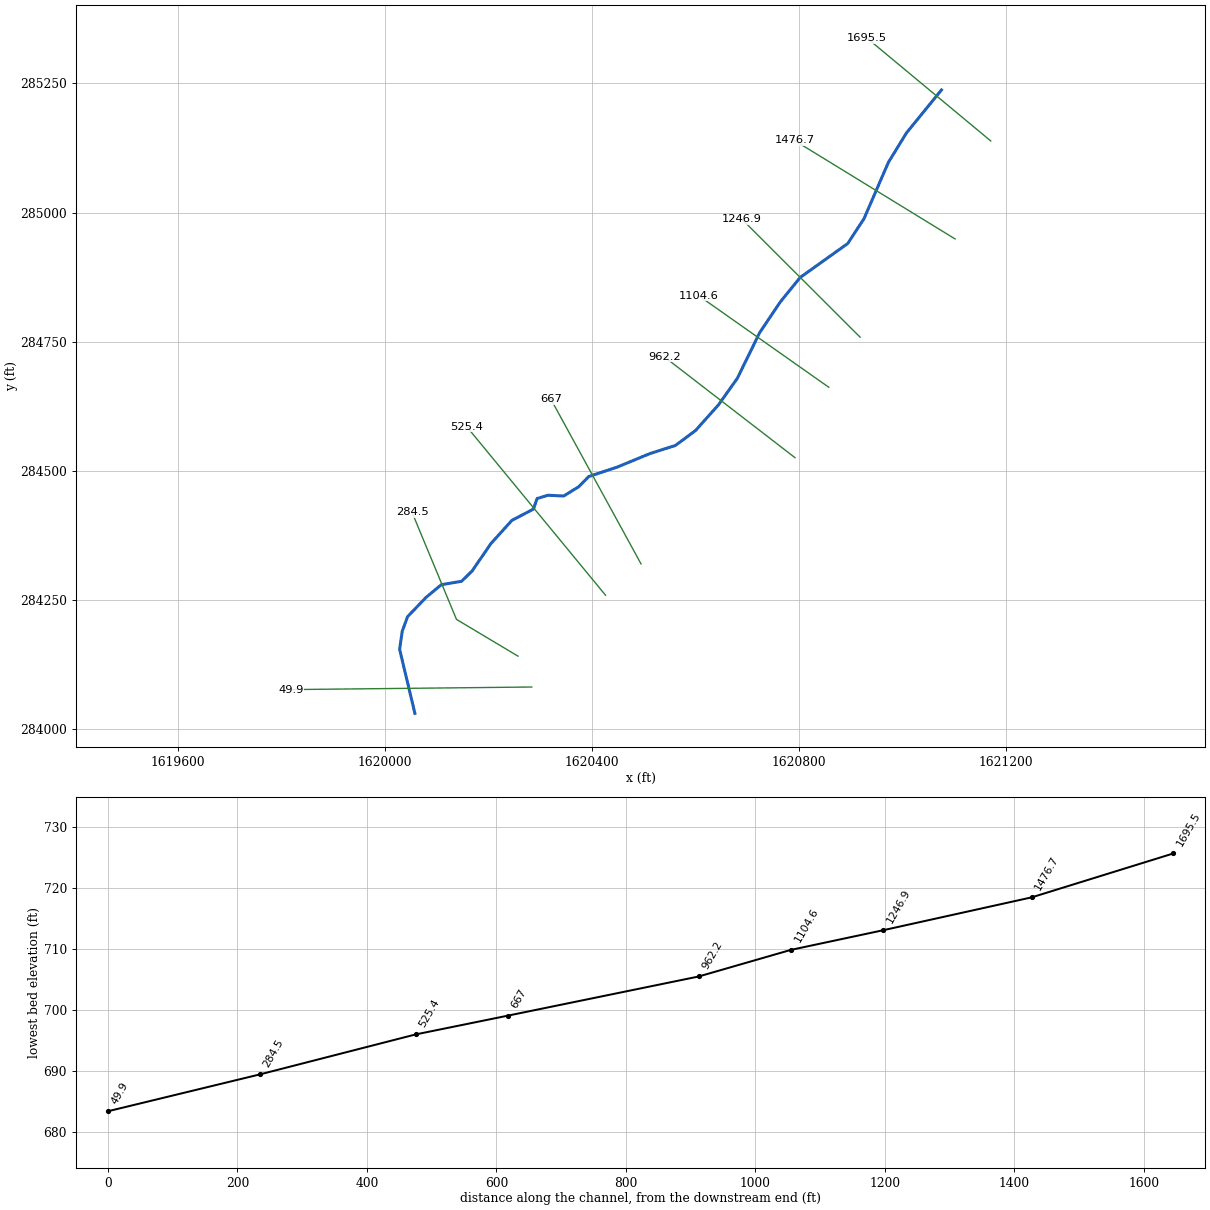
--- sprngbrch1.prj (project) ---

Proj Title=sprngbrch1
Current Plan=p01
Default Exp/Contr=0,0
English Units
Geom File=g01
Flow File=f01
Plan File=p01
BEGIN DESCRIPTION:
END DESCRIPTION:
DSS Export Rating Curves= 0
DSS Export Rating Curve Sorted= 0
DSS Export Volume Flow Curves= 0
DXF OffsetX= 0
DXF OffsetY= 0
DXF ScaleX= 0
DXF ScaleY= 0

--- sprngbrch1.p01 (plan) ---

Plan Title=Approixmate Study  - 100yr
Program Version=4.00
Geom File=g01
Flow File=f01
Subcritical Flow
K Sum by GR= 0
Std Step Tol= 0.01
Critical Tol= 0.01
Num of Std Step Trials= 20
Max Error Tol= 0.3
Flow Tol Ratio= 0.001
Split Flow NTrial= 30
Split Flow Tol= 0.02
Split Flow Ratio= 0.02
Log Output Level= 0
Friction Slope Method= 1
Unsteady Friction Slope Method= 2
Unsteady Bridges Friction Slope Method= 1
Parabolic Critical Depth
Global Vel Dist= 0 , 0 , 0
Global Log Level= 0
CheckData=True
Encroach Param=-1 ,0,0, 0
Run HTab= 0
Run UNet= 0
Run PostProcess= 0
Run WQNet= 0
UNET Theta= 0
UNET Theta Warmup= 0
UNET ZTol= 0
UNET ZSATol= 0
UNET MxIter= 0
UNET MaxInSteps= 0
UNET DtIC= 0
UNET DtMin= 0
UNET MaxCRTS= 0
UNET WFStab= 0
UNET SFStab= 0
UNET WFX= 1
UNET SFX= 1
UNET DSS MLevel= 1
UNET DZMax Abort= 0
UNET Convert EG Bridges= 0
UNET Use Existing IB Tables= 0
UNET Froude Reduction=False
UNET Froude Limit= 0
UNET Froude Power= 0
UNET Time Slicing=0,0, 5
Write IC File= 0
Echo Input=False
Echo Output=False
Write Detailed= 0
Detailed Automatic Start=False, 0
WQ ULTIMATE=-1
WQ Max Comp Step=1HOUR
WQ Output Interval=15MIN
WQ Output Selected Increments= 0
WQ Output face flow=0
WQ Output face velocity=0
WQ Output face area=0
WQ Output face dispersion=0
WQ Output cell volume=0
WQ Output cell surface area=0
WQ Output cell continuity=0
WQ Output face conc=0
WQ Output face dconc_dx=0
WQ Output face courant=0
WQ Output face peclet=0
WQ Output face adv mass=0
WQ Output face disp mass=0
WQ Output cell mass=0
WQ Output cell source sink temp=0
WQ Output cell source sink nsm=0
WQ Output MaxMinRange=-1
WQ Daily Max Min Mean=-1
WQ Daily Range=0
WQ Daily Time=0
WQ Create Restart=0
WQ Fixed Restart=0
WQ System Summary=False
Sorting and Armoring Iterations= 10
XS Update Threshold= 0.02
Hydraulics Update Threshold= 0.02
Energy Slope Method= 1
Volume Change Method= 0
XS Weighting Method= 0
Number of US Weighted Cross Sections= 1
Number of DS Weighted Cross Sections= 1
Upstream XS Weight=0.25
Main XS Weight=0.5
Downstream XS Weight=0.25
Number of DS XS's Weighted with US Boundary= 1
Upstream Boundary Weight= 1
Weight of XSs Associated with US Boundary= 0
Number of US XS's Weighted with DS Boundary= 1
Downstream Boundary Weight= 0.5
Weight of XSs Associated with DS Boundary= 0.5
Sediment Output Level= 4
Mass or Volume Output= 0
Output Increment Type= 1
Profile and TS Output Increment= 10
XS Output Flag= 0
XS Output Increment= 10
Disregard all LS=0
Disregard all Conn=0
Disregard all Breaches=0
Disregard all Pumps=0

--- sprngbrch1.f01 (steady flow) ---

Flow Title=USGS Regression Equation
Program Version=4.00
Number of Profiles= 1
Profile Names=P100yr
River Rch & RM=sprngbrch1,Main            ,1695.5
     376
River Rch & RM=sprngbrch1,Main            ,284.5
     389
Boundary for River Rch & Prof#=sprngbrch1,Main            , 1
Up Type= 0
Dn Type= 3
Dn Slope=0.019
DSS Import GetInterval= 0
DSS Import GetPeak= 0
DSS Import FillOption= 0

--- sprngbrch1.g01 (geometry) ---

Geom Title=USGS 3m DEM
Program Version=4.00

River Reach=sprngbrch1      ,Main
Reach XY= 30
     1621075.698      285237.455     1621008.041       285154.21
     1620973.041      285097.035     1620926.033      284988.188
     1620894.492      284939.943      1620802.64      284874.228
     1620764.823      284827.712     1620724.505      284767.799
     1620680.898      284678.504     1620644.028      284626.665
     1620600.021      284577.422     1620561.221      284548.624
     1620512.467       284533.08     1620448.744      284506.742
     1620393.799       284488.47     1620374.452      284468.759
     1620345.289      284450.702     1620315.071      284452.194
     1620293.813      284445.816      1620286.86      284425.334
     1620245.293      284403.653     1620204.831      284358.821
     1620167.984      284305.151     1620147.716      284285.453
      1620108.72      284278.878     1620079.573      284254.655
     1620043.467       284216.97     1620033.066      284188.475
     1620028.059      284153.743     1620057.601      284029.555

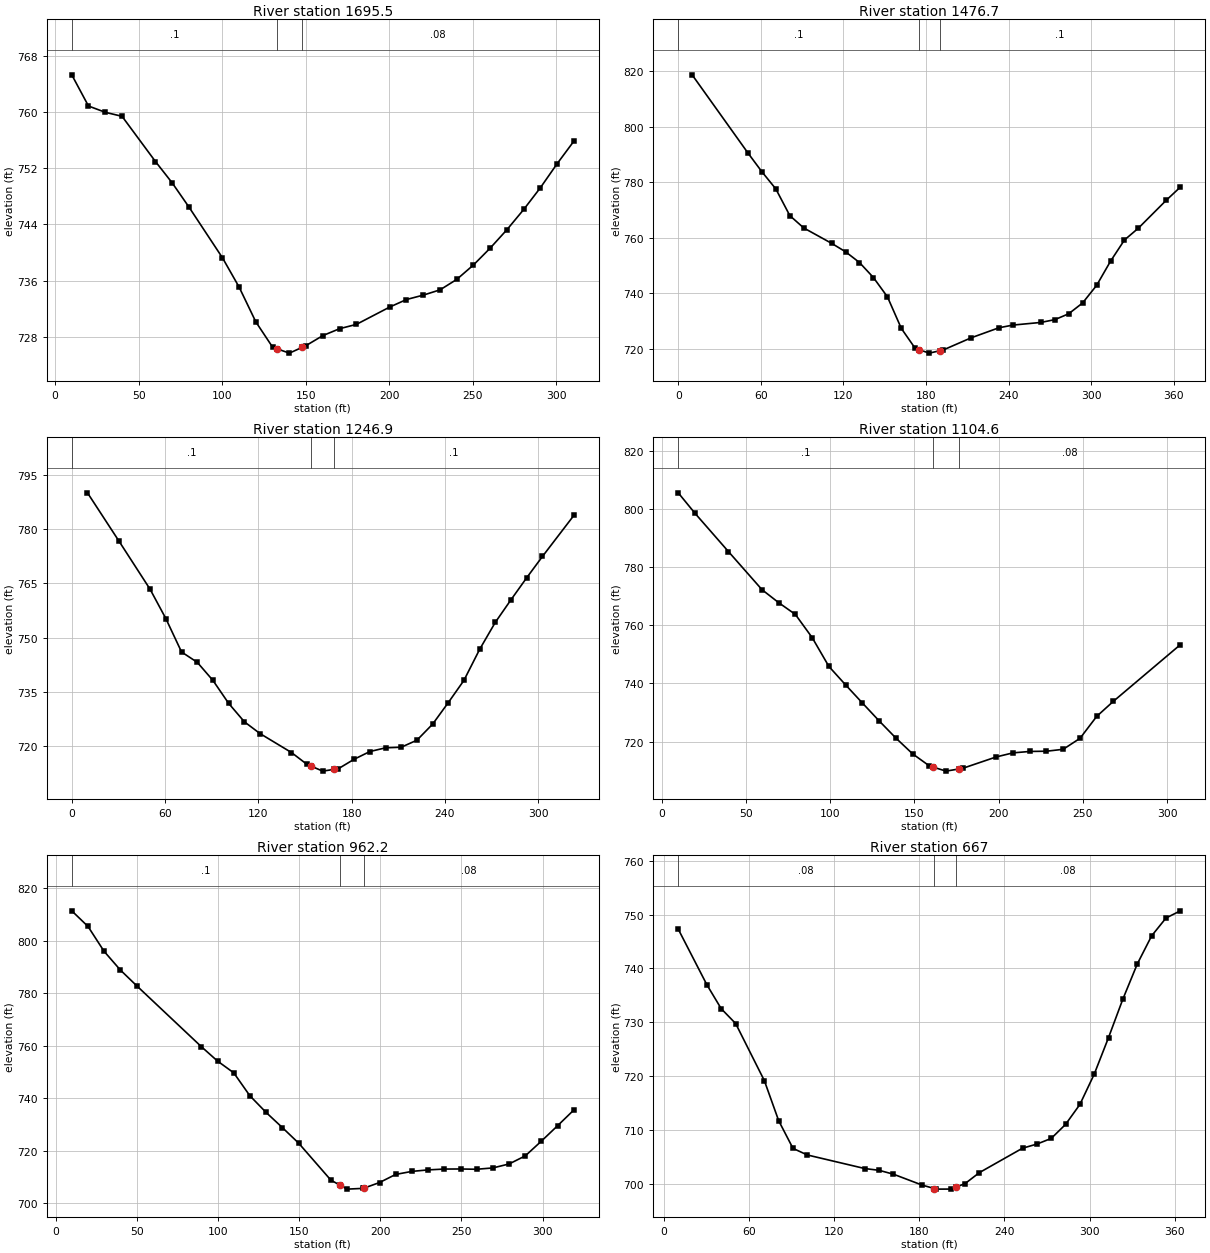
Type RM Length L Ch R = 1 ,1695.5  ,215.6,218.8,222
XS GIS Cut Line= 2
      1621170.99      285138.725     1620932.275      285337.509
#Sta/Elev= 30
      10  765.35      20   760.9    30.1     760    40.1  759.43    60.1  752.98
    70.1  749.94    80.2  746.47   100.2  739.25   110.2  735.06   120.2   730.1
   130.3  726.47   132.8  726.26   140.3  725.64   147.8  726.45   150.3  726.72
   160.3  728.14   170.4  729.13   180.4  729.74   200.4  732.22   210.4  733.29
   220.5  733.92   230.5  734.67   240.5  736.16   250.5  738.22   260.5  740.62
   270.6  743.27   280.6  746.14   290.6  749.25   300.6  752.67   310.6  755.88
#Mann= 3 , 0 , 0
      10      .1       0   132.8    .045       0   147.8     .08       0
Bank Sta=132.8,147.8
XS Rating Curve= 0 ,0
Exp/Cntr=0.3,0.1

Type RM Length L Ch R = 1 ,1476.7  ,235.1,229.8,224.5
XS GIS Cut Line= 2
     1621102.028      284948.813     1620791.264      285139.785
#Sta/Elev= 30
    10.1  818.65    50.7  790.47    60.8  783.74    70.9  777.57    81.1  767.94
    91.2  763.51   111.5  757.96   121.6  754.93   131.7  751.06   141.8  745.67
     152  738.71   162.1  727.33   172.2  720.14   174.9  719.69   182.4  718.44
   189.9  719.28   192.5  719.57   212.8  723.95     233  727.57   243.2  728.54
   263.4  729.49   273.6  730.49   283.7  732.61   293.8   736.5     304  742.84
   314.1  751.54   324.2  759.17   334.4  763.47   354.6  773.49   364.8  778.21
#Mann= 3 , 0 , 0
       0      .1       0   174.9    .045       0   189.9      .1       0
Bank Sta=174.9,189.9
XS Rating Curve= 0 ,0
Exp/Cntr=0.3,0.1

Type RM Length L Ch R = 1 ,1246.9  ,138.5,142.4,146.2
XS GIS Cut Line= 2
     1620918.386      284758.516     1620690.088      284986.815
#Sta/Elev= 30
    10.1  790.09    30.3  776.76    50.4  763.37    60.5  755.28    70.6  746.03
    80.7  743.17    90.8  738.15   100.9   731.8     111   726.7   121.1  723.43
   141.3  718.19   151.3   714.9   153.9  714.42   161.4  713.04   168.9  713.54
   171.5  713.72   181.6  716.33   191.7  718.46   201.8  719.49   211.9  719.66
     222  721.61   232.1  726.06   242.1  731.98   252.2  738.16   262.3  746.74
   272.4  754.24   282.5   760.5   292.6  766.59   302.7  772.47   322.9  783.83
#Mann= 3 , 0 , 0
       0      .1       0   153.9    .045       0   168.9      .1       0
Bank Sta=153.9,168.9
XS Rating Curve= 0 ,0
Exp/Cntr=0.3,0.1

Type RM Length L Ch R = 1 ,1104.6  ,143.4,142.4,141.4
XS GIS Cut Line= 2
     1620857.912      284661.391     1620606.368       284838.86
#Sta/Elev= 27
     9.9  805.57    19.9  798.49    39.7  785.35    59.6  772.25    69.5  767.78
    79.4  763.73    89.4  755.73    99.3  745.83   109.2  739.49   119.2  733.24
   129.1  727.11     139  721.22     149  715.75   158.9  711.62   161.3  711.18
   168.8  709.82   176.3  710.55   178.7  710.79   198.6  714.71   208.5   716.1
   218.5  716.59   228.4  716.67   238.3  717.33   248.3  721.11   258.2  728.66
   268.1  733.85   307.8  753.31
#Mann= 3 , 0 , 0
     9.9      .1       0   161.3    .045       0   176.3     .08       0
Bank Sta=161.3,176.3
XS Rating Curve= 0 ,0
Exp/Cntr=0.3,0.1

Type RM Length L Ch R = 1 ,962.2   ,304.5,295.2,285.8
XS GIS Cut Line= 2
     1620792.518      284525.009     1620539.914      284720.322
#Sta/Elev= 30
      10  811.41      20  805.46    29.9     796    39.9   788.9    49.9  782.94
    89.8  759.71    99.8  754.21   109.8  749.73   119.7  741.02   129.7  734.67
   139.7  728.91   149.7  723.01   169.6   708.9   175.1 707.008   179.6  705.46
   189.6  705.75   190.1 705.861   199.6  707.97   209.5  711.05   219.5  712.21
   229.5  712.78   239.5   713.1   249.5  713.13   259.4  713.02   269.4  713.53
   279.4  715.04   289.4  718.13   299.3  723.73   309.3  729.61   319.3  735.59
#Mann= 3 , 0 , 0
      10      .1       0   175.1    .045       0   190.1     .08       0
Bank Sta=175.1,190.1
XS Rating Curve= 0 ,0
Exp/Cntr=0.3,0.1

Type RM Length L Ch R = 1 ,667     ,136.9,141.6,145.6
XS GIS Cut Line= 2
     1620494.775       284319.28     1620320.296      284638.725
#Sta/Elev= 30
    10.1  747.29    30.3  736.96    40.4  732.52    50.6  729.76    70.8  719.17
    80.9  711.73      91  706.59   101.1  705.37   141.6  702.85   151.7  702.52
   161.8   701.8     182  699.78   190.6 699.142   192.1  699.03   202.2  699.04
   205.6 699.383   212.3  700.06   222.4   702.1   252.8  706.63   262.9  707.39
     273  708.44   283.1  711.04   293.2  714.74   303.3  720.36   313.4  727.16
   323.5   734.3   333.7  740.84   343.8  746.05   353.9  749.35     364  750.69
#Mann= 3 , 0 , 0
    10.1     .08       0   190.6    .045       0   205.6     .08       0
Bank Sta=190.6,205.6
XS Rating Curve= 0 ,0
Exp/Cntr=0.3,0.1

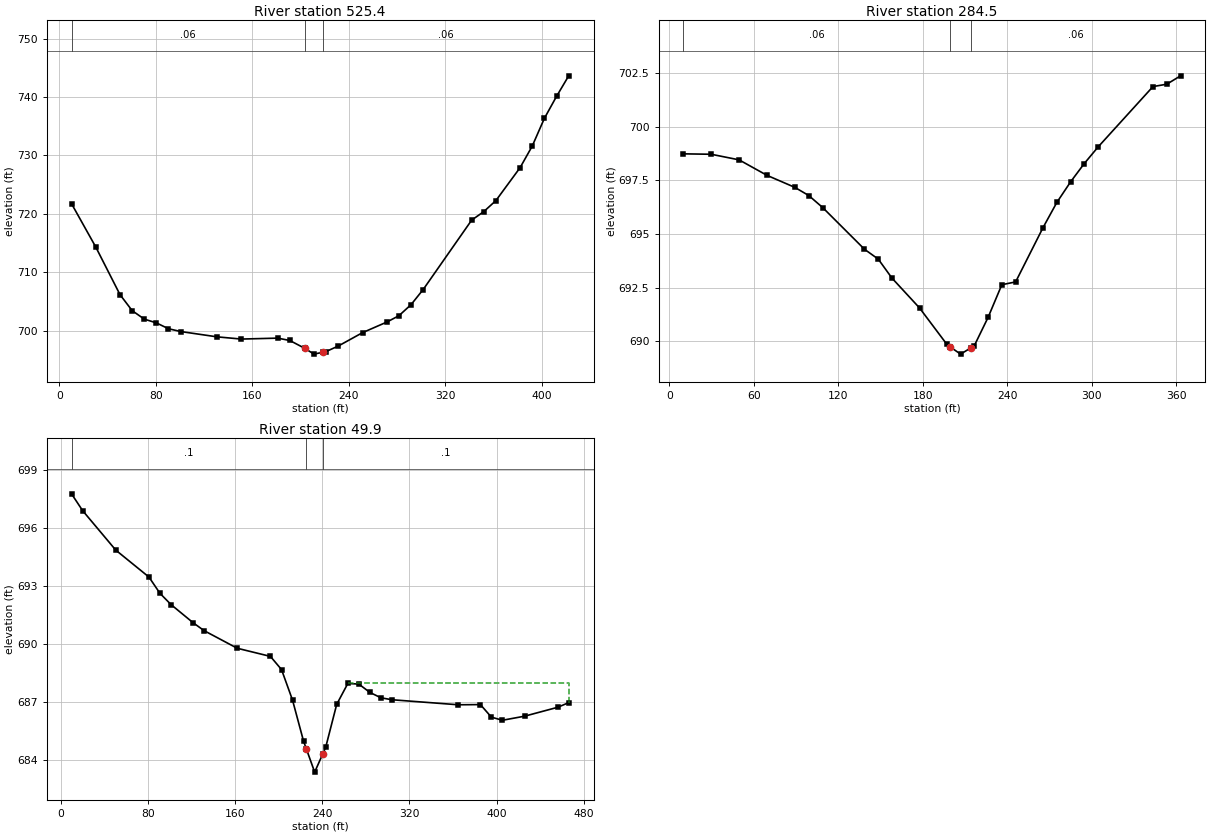
Type RM Length L Ch R = 1 ,525.4   ,247.6,240.9,234.5
XS GIS Cut Line= 2
     1620426.199      284258.516      1620157.97      284584.905
#Sta/Elev= 30
    10.1  721.74    30.2  714.32    50.3  706.16    60.4  703.42    70.4  701.97
    80.5  701.32    90.5  700.32   100.6  699.84   130.8  698.93   150.9  698.55
   181.1  698.71   191.1  698.31   203.7  696.95   211.2  695.97   218.7   696.3
   221.3  696.42   231.3  697.35   251.5  699.65   271.6  701.46   281.6  702.54
   291.7  704.44   301.8  707.04     342  718.92   352.1  720.39   362.1  722.27
   382.2  727.92   392.3  731.63   402.3  736.35   412.4  740.12   422.5  743.64
#Mann= 3 , 0 , 0
    10.1     .06       0   203.7    .045       0   218.7     .06       0
Bank Sta=203.7,218.7
XS Rating Curve= 0 ,0
Exp/Cntr=0.3,0.1

Type RM Length L Ch R = 1 ,284.5   ,207.5,234.6,261.8
XS GIS Cut Line= 3
     1620256.928      284140.461     1620138.004      284211.641
     1620052.067      284419.106
#Sta/Elev= 27
     9.9  698.73    29.7  698.71    49.5  698.45    69.3  697.73    89.1  697.17
      99  696.79   108.9  696.23   138.6  694.29   148.4  693.83   158.1  692.95
   177.7  691.56   197.2  689.86   199.4  689.75   206.9  689.41   214.4  689.71
   216.7  689.81   226.5  691.13   236.2  692.64     246  692.77   265.5   695.3
   275.3  696.47   285.1  697.43   294.8  698.28   304.6  699.05   343.6  701.86
   353.4  701.97   363.2  702.36
#Mann= 3 , 0 , 0
     9.9     .06       0   199.4    .045       0   214.4     .06       0
Bank Sta=199.4,214.4
XS Rating Curve= 0 ,0
Exp/Cntr=0.3,0.1

Type RM Length L Ch R = 1 ,49.9    ,44.8,49.9,55
XS GIS Cut Line= 2
      1620283.62      284080.632      1619817.52      284075.636
#Sta/Elev= 30
    10.1  697.75    20.3  696.88    50.7  694.84    81.1  693.45    91.2  692.61
   101.3  692.03   121.6  691.09   131.7  690.68   162.1  689.77   192.5  689.35
   202.7  688.67   212.8  687.09   222.9  684.97   225.6  684.55   233.1  683.37
   240.6  684.32   243.2  684.65   253.3  686.87   263.5  687.95   273.6  687.92
   283.7  687.49   293.9  687.21     304  687.11   364.8  686.85   385.1  686.86
   395.2  686.21   405.3  686.05   425.6  686.26     456  686.72   466.1  686.96
#Mann= 3 , 0 , 0
    10.1      .1       0   225.6    .045       0   240.6      .1       0
#XS Ineff= 2 , 0
       0                   263.5       0  687.95
Permanent Ineff=
       F       F
Bank Sta=225.6,240.6
XS Rating Curve= 0 ,0
Exp/Cntr=0.3,0.1

Chan Stop Cuts=-1
Use User Specified Reach Order=0